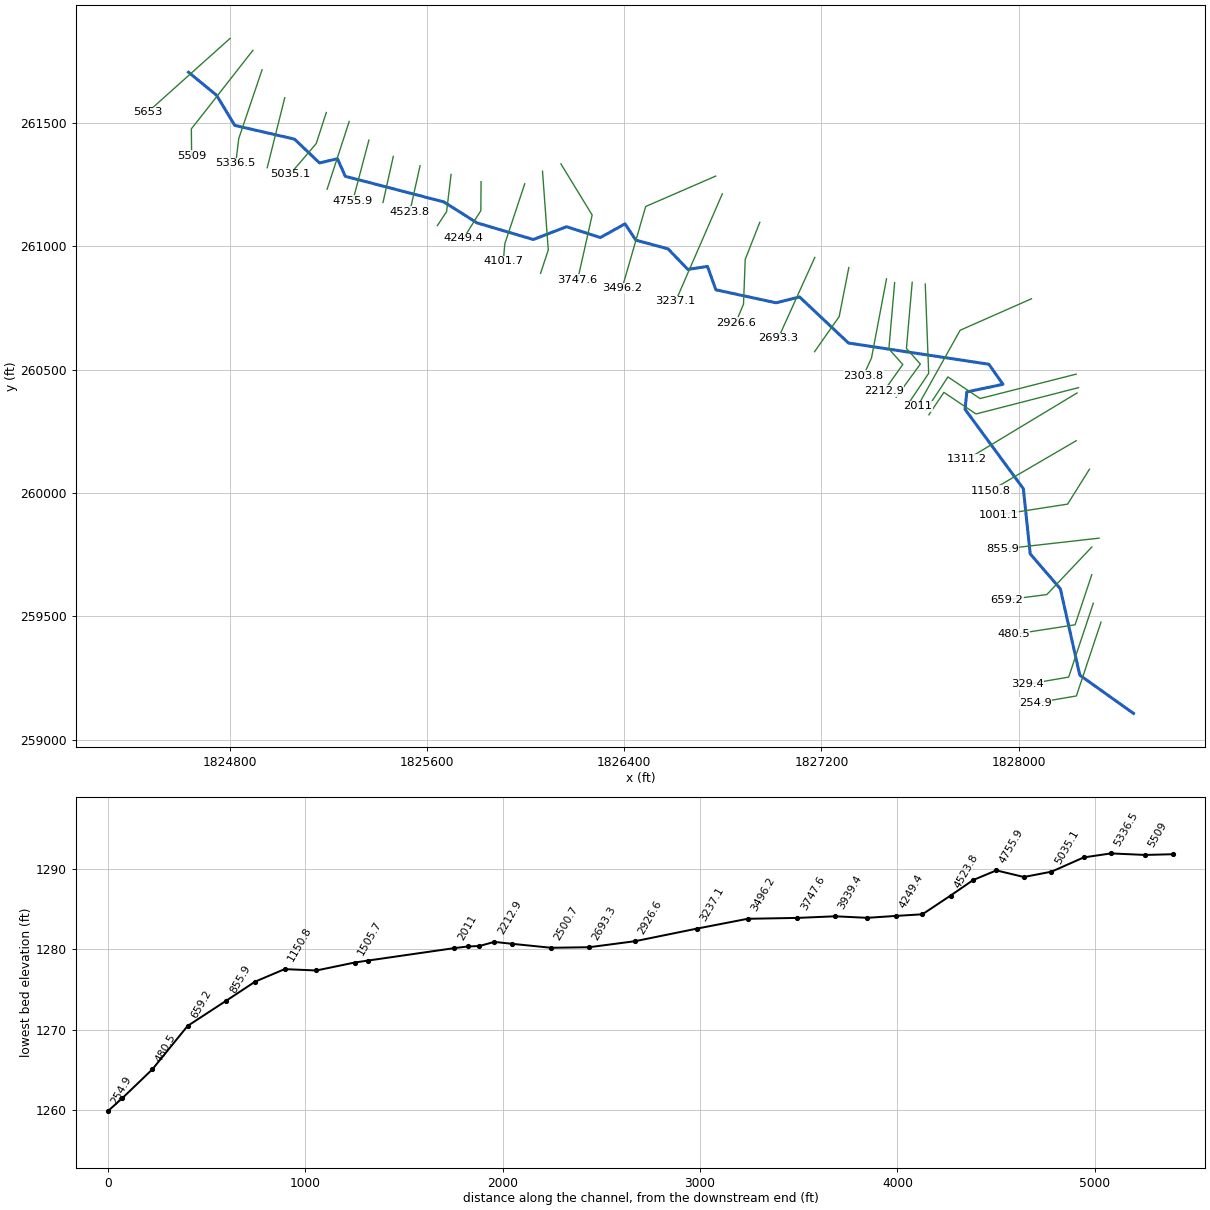
--- MITCHELLRN.prj (project) ---

Proj Title=MITCHELLRN
Current Plan=p01
Default Exp/Contr=0,0
English Units
Geom File=g01
Flow File=f01
Plan File=p01
BEGIN DESCRIPTION:
END DESCRIPTION:
DSS Export Rating Curves= 0
DSS Export Rating Curve Sorted= 0
DSS Export Volume Flow Curves= 0
DXF OffsetX= 0
DXF OffsetY= 0
DXF ScaleX= 0
DXF ScaleY= 0

--- MITCHELLRN.p01 (plan) ---

Plan Title=Floodplain
Program Version=4.00
Geom File=g01
Flow File=f01
K Sum by GR=0
Std Step Tol=0.01
Critical Tol=0.01
Num of Std Step Trials=20
Max Error Tol=0.3
Flow Tol Ratio=0.001
Split Flow NTrial=30
Split Flow Tol=0.02
Split Flow Ratio=0.02
Log Output Level=0
Friction Slope Method=1
Unsteady Friction Slope Method=2
Unsteady Bridges Friction Slope Method=1
Global Log Level=0
CheckData=False
Run HTab=0
Run UNet=0
Run PostProcess=0
UNET Theta=0
UNET Theta Warmup=0
UNET ZTol=0
UNET ZSATol=0
UNET MxIter=0
UNET MaxInSteps=0
UNET DtIC=0
UNET DtMin=0
UNET MaxCRTS=0
UNET WFStab=0
UNET SFStab=0
UNET WFX=0
UNET SFX=0
UNET DSS MLevel=0
UNET DZMax Abort=0
UNET Convert EG Bridges=0
UNET Use Existing IB Tables=0
UNET Froude Limit=0
UNET Froude Power=0
Write IC File=0
Echo Input=False
Echo Output=False
Write Detailed=0

--- MITCHELLRN.f01 (steady flow) ---

Flow Title=NFF Regression Equation
Program Version=4.00
Number of Profiles=1
Profile Names=P100yr
River Rch & RM=MITCHELLRN,Main      ,5653
544.7043
River Rch & RM=MITCHELLRN,Main      ,3747.6
564.8252
River Rch & RM=MITCHELLRN,Main      ,3496.2
806.0817
River Rch & RM=MITCHELLRN,Main      ,480.5
839.4352
River Rch & RM=MITCHELLRN,Main      ,254.9
840.3147
Boundary for River Rch & Prof#=MITCHELLRN,Main      ,1
Up Type=0
Dn Type=3
Dn Slope=0.02524

--- MITCHELLRN.g01 (geometry) ---

Geom Title=USGS 10m DEM
Program Version=4.10

River Reach=MITCHELLRN      ,Main
Reach XY= 30
     1824633.369      261706.132     1824747.084      261612.729
     1824821.007      261490.335     1825063.064      261434.887
     1825164.496      261338.319     1825237.358      261355.363
      1825269.13      261284.043     1825668.918      261180.172
     1825803.662      261095.045       1826031.5       261027.82
     1826166.314      261079.623     1826303.508      261035.776
     1826403.486       261091.27     1826447.432      261025.186
      1826578.11      260989.797      1826658.06      260906.654
     1826737.728      260918.684     1826771.954      260823.893
      1827015.73      260771.237     1827111.147      260794.977
     1827309.411      260608.172     1827878.938      260522.062
     1827936.071      260440.702     1827789.564      260409.914
     1827782.154      260339.595     1828018.694      260017.424
      1828046.39      259753.484     1828168.845      259611.294
     1828247.432      259261.644     1828465.118      259106.626

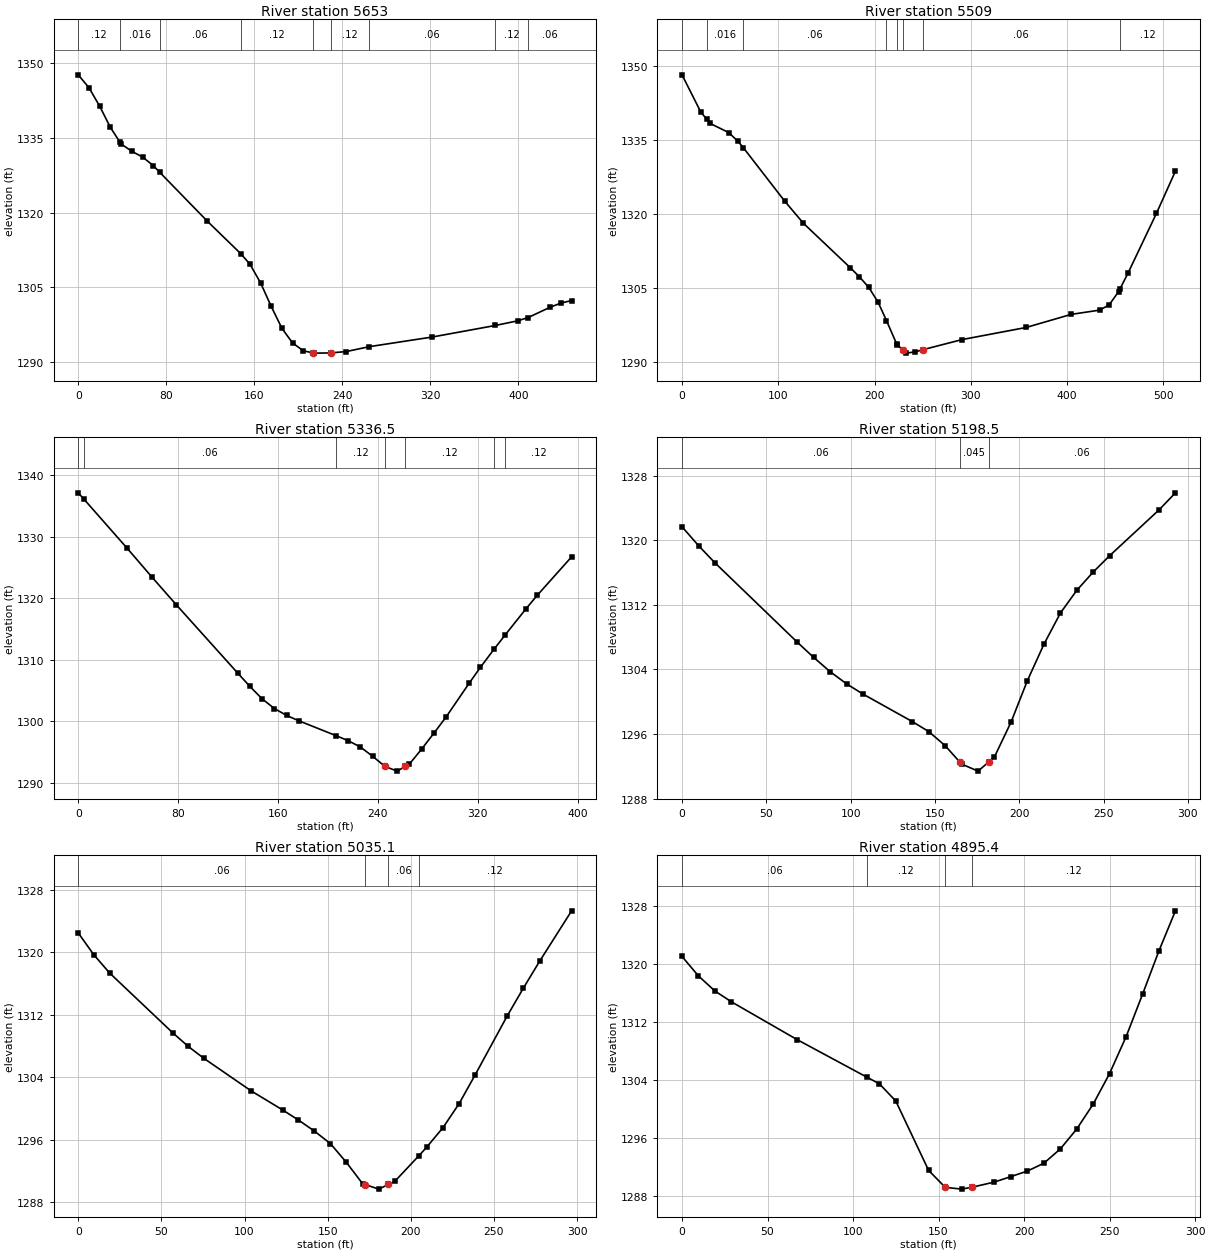
Type RM Length L Ch R = 1 ,5653    ,139.9,144.1,148.3
XS GIS Cut Line= 2
     1824802.245      261843.439      1824468.11      261544.467
#Sta/Elev= 30
       0 1347.72     9.8 1345.13    19.5 1341.42    29.2 1337.17   37.741334.259
      39 1333.83    48.7 1332.36    58.5  1331.2    68.2 1329.49   73.911328.179
     117 1318.39  147.541311.824     156  1309.7   165.7 1305.94   175.4 1301.19
   185.2 1296.76   194.9 1293.83   204.7 1292.27  213.191291.869   214.4 1291.81
  229.291291.848   243.7 1292.13  264.591293.112   321.6 1295.04  378.961297.361
   399.6 1298.31  408.921298.966   428.9 1301.03   438.6 1301.86   448.4 1302.37
#Mann= 9 ,-1 , 0
       0     .12       0   37.74    .016       0   73.91     .06       0
  147.54     .12       0  213.19    .045       0  229.29     .12       0
  264.59     .06       0  378.96     .12       0  408.92     .06       0
Bank Sta=213.19,229.29
XS Rating Curve= 0 ,0
Exp/Cntr=0.3,0.1

Type RM Length L Ch R = 1 ,5509    ,164.8,172.5,179.9
XS GIS Cut Line= 4
     1824894.349      261794.681      1824703.11       261550.18
       1824644.9      261476.487     1824646.062      261368.251
#Sta/Elev= 30
       0 1348.17    19.4 1340.66   25.491339.191    29.1 1338.32    48.5 1336.46
    58.2 1334.67   63.711333.386   106.7 1322.54   126.1 1318.06   174.6 1309.08
   184.3  1307.2     194 1305.06   203.7 1302.05  212.411298.324   223.1 1293.53
  223.721293.414  229.371292.359   232.8 1291.72   242.5 1291.98  249.991292.404
     291 1294.47   357.4 1296.92   404.3 1299.58   433.8 1300.44   443.7 1301.49
   453.5 1304.18  454.951304.735   463.4 1307.97   492.9 1320.08   512.6 1328.63
#Mann= 8 ,-1 , 0
       0     .12       0   25.49    .016       0   63.71     .06       0
  212.41     .12       0  223.72     .06       0  229.37    .045       0
  249.99     .06       0  454.95     .12       0
Bank Sta=229.37,249.99
XS Rating Curve= 0 ,0
Exp/Cntr=0.3,0.1

Type RM Length L Ch R = 1 ,5336.5  ,136.1,137.9,139.7
XS GIS Cut Line= 3
     1824931.652      261715.908     1824837.034      261436.828
     1824824.881      261337.001
#Sta/Elev= 29
       0 1337.18    4.441336.183    39.3 1328.14    58.9 1323.51    78.6 1318.96
   127.7 1307.87   137.5 1305.69   147.3 1303.67   157.2 1302.08     167 1300.96
   176.8 1300.09  206.661297.669   216.1 1296.87   225.9 1295.85   235.8 1294.33
   245.6 1292.69   255.4 1291.91  262.13 1292.69   265.2 1293.04     275 1295.48
   284.9 1298.08   294.7 1300.73     313 1306.17   322.1 1308.78  333.24 1311.79
  342.221314.124   358.7 1318.33   367.8 1320.54   395.2 1326.77
#Mann= 7 ,-1 , 0
       0    .016       0    4.44     .06       0  206.66     .12       0
   245.6    .045       0  262.13     .12       0  333.24     .06       0
  342.22     .12       0
Bank Sta=245.6,262.13
XS Rating Curve= 0 ,0
Exp/Cntr=0.3,0.1

Type RM Length L Ch R = 1 ,5198.5  ,174.1,163.4,152.7
XS GIS Cut Line= 2
     1825023.666      261602.626     1824952.485      261318.772
#Sta/Elev= 25
       0 1321.66     9.8 1319.32    19.5  1317.2    68.3 1307.38      78  1305.5
    87.8 1303.73    97.6 1302.21   107.3 1300.95   136.6 1297.54   146.3 1296.31
   156.1 1294.55  164.591292.563   165.8 1292.28   175.6 1291.41  182.011292.577
   185.3 1293.18   195.1 1297.47   204.8 1302.61   214.6 1307.11   224.4 1310.98
   234.1 1313.79   243.9 1316.07   253.6 1318.08   282.9 1323.75   292.6 1325.86
#Mann= 3 ,-1 , 0
       0     .06       0  164.59    .045       0  182.01     .06       0
Bank Sta=164.59,182.01
XS Rating Curve= 0 ,0
Exp/Cntr=0.3,0.1

Type RM Length L Ch R = 1 ,5035.1  ,130.3,139.7,150
XS GIS Cut Line= 3
     1825192.069       261542.73      1825151.27      261416.862
     1825044.499      261291.862
#Sta/Elev= 26
       0 1322.51     9.4  1319.7    18.9 1317.36    56.7 1309.72    66.2 1307.94
    75.6 1306.41     104 1302.24   122.9  1299.8   132.3 1298.52     142 1297.09
   151.7 1295.47   161.3 1293.06     171 1290.34  172.691290.218   180.7 1289.64
  186.531290.236   190.3 1290.62  204.871293.925   209.7 1295.06   219.4 1297.54
     229 1300.59   238.7  1304.3     258 1311.87   267.7 1315.43   277.4 1318.85
   296.7 1325.34
#Mann= 4 ,-1 , 0
       0     .06       0  172.69    .045       0  186.53     .06       0
  204.87     .12       0
Bank Sta=172.69,186.53
XS Rating Curve= 0 ,0
Exp/Cntr=0.3,0.1

Type RM Length L Ch R = 1 ,4895.4  ,137.9,139.5,139.3
XS GIS Cut Line= 2
     1825284.951      261506.272     1825195.541      261231.967
#Sta/Elev= 24
       0  1321.1     9.6 1318.41    19.2 1316.34    28.8 1314.85    67.3 1309.62
   108.41304.395   115.4 1303.52     125 1301.14   144.2 1291.56   153.9 1289.23
   163.5 1288.98  169.741289.253   182.7 1289.96   192.3 1290.71     202 1291.48
   211.6 1292.56   221.2 1294.53   230.8 1297.28   240.4 1300.71     250 1304.94
   259.7 1310.05   269.3  1315.9   278.9  1321.9   288.5  1327.4
#Mann= 4 ,-1 , 0
       0     .06       0   108.4     .12       0   153.9    .045       0
  169.74     .12       0
Bank Sta=153.9,169.74
XS Rating Curve= 0 ,0
Exp/Cntr=0.3,0.1

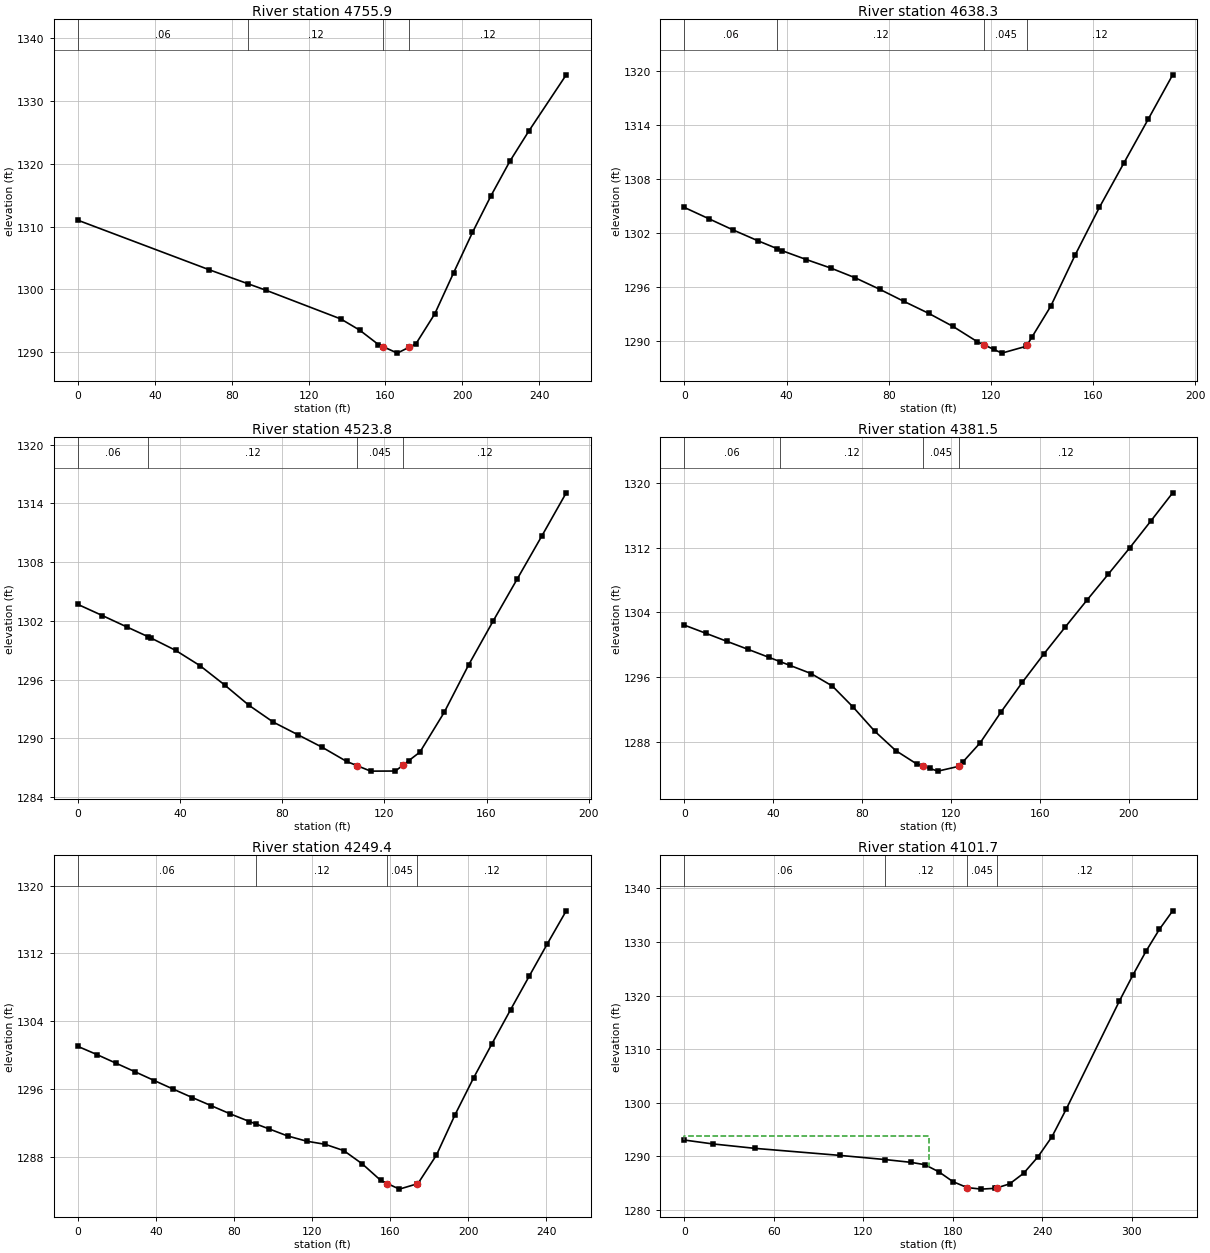
Type RM Length L Ch R = 1 ,4755.9  ,116.7,117.6,118.5
XS GIS Cut Line= 2
     1825364.812      261430.751     1825299.708      261185.092
#Sta/Elev= 18
       0    1311    68.4 1303.09    88.71300.843    97.8 1299.84   136.8 1295.25
   146.6 1293.47   156.4 1291.16  158.94 1290.81   166.2  1289.8  172.521290.771
   175.9 1291.29   185.7 1296.07   195.5 1302.62   205.3 1309.05     215 1314.94
   224.8 1320.43   234.6 1325.21   254.1  1334.2
#Mann= 4 ,-1 , 0
       0     .06       0    88.7     .12       0  158.94    .045       0
  172.52     .12       0
Bank Sta=158.94,172.52
XS Rating Curve= 0 ,0
Exp/Cntr=0.3,0.1

Type RM Length L Ch R = 1 ,4638.3  ,114.4,114.4,114.4
XS GIS Cut Line= 2
      1825463.77      261364.779     1825422.103      261178.147
#Sta/Elev= 26
       0 1304.83     9.6 1303.57    19.1 1302.32    28.7 1301.13   36.371300.234
    38.2 1300.02    47.8 1299.02    57.4 1298.07    66.9 1296.99    76.5 1295.71
      86 1294.36    95.6 1293.04   105.2 1291.57   114.7 1289.87  117.371289.517
   121.2 1289.01   124.3  1288.6   133.9 1289.37   134.31289.556   136.2 1290.44
   143.4  1293.8     153 1299.53   162.5 1304.84   172.1 1309.79   181.7 1314.71
   191.2 1319.61
#Mann= 4 ,-1 , 0
       0     .06       0   36.37     .12       0  117.37    .045       0
   134.3     .12       0
Bank Sta=117.37,134.3
XS Rating Curve= 0 ,0
Exp/Cntr=0.3,0.1

Type RM Length L Ch R = 1 ,4523.8  ,140,142.3,144.6
XS GIS Cut Line= 2
     1825572.277      261326.585      1825530.61      261139.953
#Sta/Elev= 25
       0 1303.68     9.6 1302.54    19.1 1301.39   27.621300.369    28.7 1300.24
    38.2    1299    47.8 1297.43    57.4 1295.47    66.9  1293.4    76.5 1291.67
      86  1290.4    95.6 1289.11   105.2 1287.66  109.431287.214   114.6 1286.67
   124.3 1286.68  127.181287.261   129.6 1287.75   133.9 1288.61   143.4 1292.66
     153 1297.52   162.5 1301.95   172.1 1306.32   181.7 1310.69   191.2 1315.07
#Mann= 4 ,-1 , 0
       0     .06       0   27.62     .12       0  109.43    .045       0
  127.18     .12       0
Bank Sta=109.43,127.18
XS Rating Curve= 0 ,0
Exp/Cntr=0.3,0.1

Type RM Length L Ch R = 1 ,4381.5  ,142,132.1,122
XS GIS Cut Line= 3
     1825698.145      261291.862     1825679.916      261140.821
      1825642.59      261084.397
#Sta/Elev= 28
       0 1302.42     9.5 1301.43      19 1300.43    28.5 1299.44      38 1298.44
   43.091297.904    47.5 1297.44      57 1296.43    66.6 1294.88    76.1 1292.23
    85.6 1289.31    95.1  1286.9   104.6 1285.23  107.331284.976   110.5 1284.68
   114.1 1284.35   123.6 1284.95   125.5 1285.53   133.1 1287.84   142.6  1291.7
   152.1 1295.34   161.8 1298.85   171.5 1302.21   181.1 1305.48   190.8 1308.73
   200.5    1312   210.1 1315.36   219.8  1318.8
#Mann= 4 ,-1 , 0
       0     .06       0   43.09     .12       0  107.33    .045       0
   123.6     .12       0
Bank Sta=107.33,123.6
XS Rating Curve= 0 ,0
Exp/Cntr=0.3,0.1

Type RM Length L Ch R = 1 ,4249.4  ,142.3,147.7,153.1
XS GIS Cut Line= 3
     1825819.673      261262.348     1825818.805      261145.161
     1825748.492      261032.314
#Sta/Elev= 30
       0    1301     9.8 1300.03    19.5 1299.02    29.3    1298    39.1 1296.97
    48.8 1295.96    58.6 1294.96    68.4 1293.99    78.1 1293.03    87.9 1292.13
    91.41291.826    97.7 1291.28   107.4 1290.43   117.2 1289.81   126.7 1289.44
   136.2  1288.7   145.7 1287.13   155.2 1285.17   158.6  1284.8   164.7 1284.15
   173.6 1284.76   174.2  1284.8   183.7 1288.17   193.2 1292.92   202.7 1297.27
   212.2 1301.34   221.7 1305.34   231.2 1309.28   240.6 1313.15   250.2 1317.01
#Mann= 4 ,-1 , 0
       0     .06       0    91.4     .12       0   158.6    .045       0
   173.6     .12       0
Bank Sta=158.6,173.6
XS Rating Curve= 0 ,0
Exp/Cntr=0.3,0.1

Type RM Length L Ch R = 1 ,4101.7  ,153.3,162.3,171.1
XS GIS Cut Line= 3
     1825996.756      261253.668     1825916.027      261010.612
     1825909.951      260939.432
#Sta/Elev= 23
       0 1293.06      19 1292.34    47.4 1291.51   104.3  1290.2  134.841289.418
   151.8 1288.91   161.3 1288.47   170.7 1287.14   180.2  1285.3   189.7  1284.2
   199.2 1283.91   208.7 1284.07  209.571284.141   218.2 1284.89   227.6 1286.87
   237.1  1289.9   246.6 1293.68   256.1 1298.79   291.8 1318.96   300.8 1323.77
   309.7 1328.27   318.6 1332.32   327.6  1335.8
#Mann= 4 ,-1 , 0
       0     .06       0  134.84     .12       0   189.7    .045       0
  209.57     .12       0
#XS Ineff= 2 , 0
          163.98 1293.78
Permanent Ineff=
       F       F
Bank Sta=189.7,209.57
XS Rating Curve= 0 ,0
Exp/Cntr=0.3,0.1

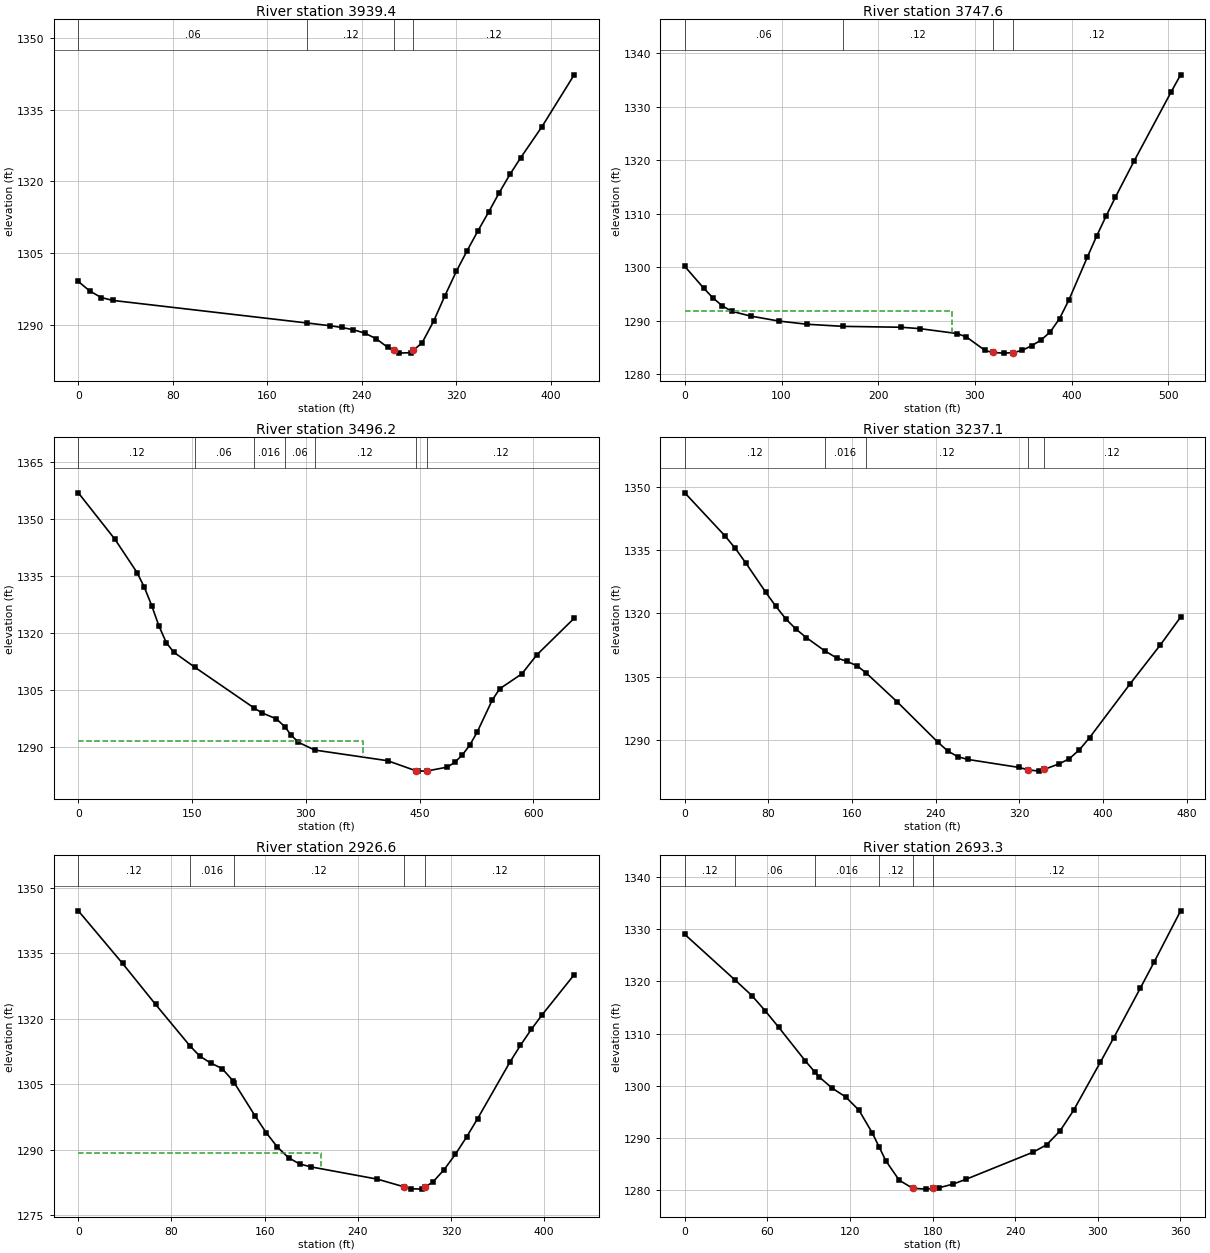
Type RM Length L Ch R = 1 ,3939.4  ,199.5,191.9,184.2
XS GIS Cut Line= 3
     1826068.805      261304.883     1826092.242      260985.439
     1826060.992      260890.821
#Sta/Elev= 27
       0 1299.08     9.7 1297.08    19.4 1295.72    29.1 1295.12     1941290.393
   213.5 1289.82   223.2 1289.46     233 1288.98   242.6 1288.29   252.4 1287.09
   262.1  1285.3  267.331284.656   271.8  1284.1   281.5  1284.2  283.66 1284.66
   291.2 1286.26   300.9 1290.75   310.6 1296.14   320.3 1301.25   329.4 1305.54
   338.4 1309.61   347.5 1313.56   356.5 1317.62   365.6 1321.46   374.6  1324.9
   392.8 1331.46     420 1342.27
#Mann= 4 ,-1 , 0
       0     .06       0     194     .12       0  267.33    .045       0
  283.66     .12       0
Bank Sta=267.33,283.66
XS Rating Curve= 0 ,0
Exp/Cntr=0.3,0.1

Type RM Length L Ch R = 1 ,3747.6  ,253.9,251.3,242.7
XS GIS Cut Line= 3
     1826143.458      261334.397     1826270.194      261126.932
     1826211.166      260863.911
#Sta/Elev= 30
       0 1300.12    19.4 1296.08    29.2 1294.21    38.9 1292.72    48.6 1291.72
    68.1 1290.83    97.2  1289.9   126.4  1289.3  164.011288.905   223.7 1288.74
   243.1 1288.48   281.6 1287.56   291.2 1286.92   310.5  1284.4  318.481284.018
   329.8  1283.9   339.4 1283.99     349 1284.43   358.6 1285.28   368.3 1286.33
   377.9 1287.87   387.5 1290.36   397.2 1293.85   416.4 1301.92     426 1305.85
   435.7 1309.56   445.3 1313.08   464.5 1319.79     503 1332.79   512.7 1335.95
#Mann= 4 ,-1 , 0
       0     .06       0  164.01     .12       0  318.48    .045       0
   339.4     .12       0
#XS Ineff= 2 , 0
          276.78 1291.86
Permanent Ineff=
       F       F
Bank Sta=318.48,339.4
XS Rating Curve= 0 ,0
Exp/Cntr=0.3,0.1

Type RM Length L Ch R = 1 ,3496.2  ,261.5,259.2,256.5
XS GIS Cut Line= 3
     1826771.062      261284.918     1826487.208      261161.654
     1826391.721      260830.925
#Sta/Elev= 30
       0 1356.79    48.4 1344.57    77.4 1335.88      87 1332.03    96.7 1327.23
   106.4 1321.79     116 1317.49   125.7    1315  153.711311.026  231.011300.453
   241.8  1299.1   261.1  1297.5  272.251295.443   280.4 1293.27   290.1 1291.36
  311.541289.322   407.8 1286.52  444.881283.891   447.2 1283.79  459.821283.837
   486.5 1284.84   496.3 1286.11   506.2 1288.01     516 1290.59   525.8 1294.01
   545.5 1302.34   555.4 1305.37   584.8 1309.32   604.5 1314.29   653.7 1323.89
#Mann= 7 ,-1 , 0
       0     .12       0  153.71     .06       0  231.01    .016       0
  272.25     .06       0  311.54     .12       0  444.88    .045       0
  459.82     .12       0
#XS Ineff= 2 , 0
          375.64 1291.76
Permanent Ineff=
       F       F
Bank Sta=444.88,459.82
XS Rating Curve= 0 ,0
Exp/Cntr=0.3,0.1

Type RM Length L Ch R = 1 ,3237.1  ,302.6,310.4,309.2
XS GIS Cut Line= 2
     1826797.971      261212.869     1826608.735      260777.973
#Sta/Elev= 30
       0 1348.57    38.7 1338.28    48.4 1335.37    58.1 1332.02    77.4 1324.99
    87.1 1321.65    96.8 1318.61   106.5 1316.22   116.2 1314.24  133.821311.098
   145.2 1309.42   154.9 1308.61   164.6 1307.57  173.16 1305.92   203.3 1298.96
     242 1289.44   251.7 1287.31   261.3 1285.97     271 1285.32   319.4 1283.45
   328.7 1282.86   338.8 1282.56   343.7 1282.96   358.1 1284.29   367.8  1285.5
   377.5 1287.63   387.2  1290.5   425.9 1303.24   454.9 1312.49   474.3  1319.1
#Mann= 5 ,-1 , 0
       0     .12       0  133.82    .016       0  173.16     .12       0
   328.7    .045       0   343.7     .12       0
Bank Sta=328.7,343.7
XS Rating Curve= 0 ,0
Exp/Cntr=0.3,0.1

Type RM Length L Ch R = 1 ,2926.6  ,241,233.3,222.9
XS GIS Cut Line= 4
     1826949.881      261097.418     1826890.853      260947.244
     1826883.909      260765.821     1826851.791      260689.432
#Sta/Elev= 30
       0 1344.74      38 1332.69    66.4 1323.29   95.611313.892   104.4 1311.44
   113.9 1309.86   123.4 1308.63   132.9  1305.8  133.811305.416   151.9 1297.72
   161.4 1293.91   170.9 1290.66   180.5  1288.2     190 1286.78   199.6 1286.11
   256.9 1283.29  280.091281.508   285.6  1281.1   295.1 1281.01  297.831281.489
   304.7  1282.7   314.2  1285.5   323.8 1288.98   333.4 1292.94   342.9 1297.16
   370.5 1310.04   379.7 1313.96     389 1317.59   398.2  1320.9   425.8  1330.1
#Mann= 5 ,-1 , 0
       0     .12       0   95.61    .016       0  133.81     .12       0
  280.09    .045       0  297.83     .12       0
#XS Ineff= 2 , 0
          208.46 1289.22
Permanent Ineff=
       F       F
Bank Sta=280.09,297.83
XS Rating Curve= 0 ,0
Exp/Cntr=0.3,0.1

Type RM Length L Ch R = 1 ,2693.3  ,196.9,192.6,189.1
XS GIS Cut Line= 2
     1827172.971      260955.057     1827024.534      260626.932
#Sta/Elev= 30
       0    1329   36.521320.262    48.7  1317.3    58.4 1314.38    68.1 1311.26
    87.6 1304.77    94.31302.712    97.3 1301.79   107.1 1299.56   116.8 1297.92
   126.5 1295.36   136.3 1290.95  141.311288.233     146 1285.69   155.7 1281.97
   165.5 1280.42   175.2 1280.26  180.471280.411   184.9 1280.54   194.7 1281.21
   204.4 1282.16   253.1 1287.35   262.8 1288.75   272.5 1291.39   282.3 1295.31
   301.7 1304.49   311.5 1309.21   330.9 1318.75   340.7 1323.63   360.1 1333.51
#Mann= 6 ,-1 , 0
       0     .12       0   36.52     .06       0    94.3    .016       0
  141.31     .12       0   165.5    .045       0  180.47     .12       0
Bank Sta=165.5,180.47
XS Rating Curve= 0 ,0
Exp/Cntr=0.3,0.1

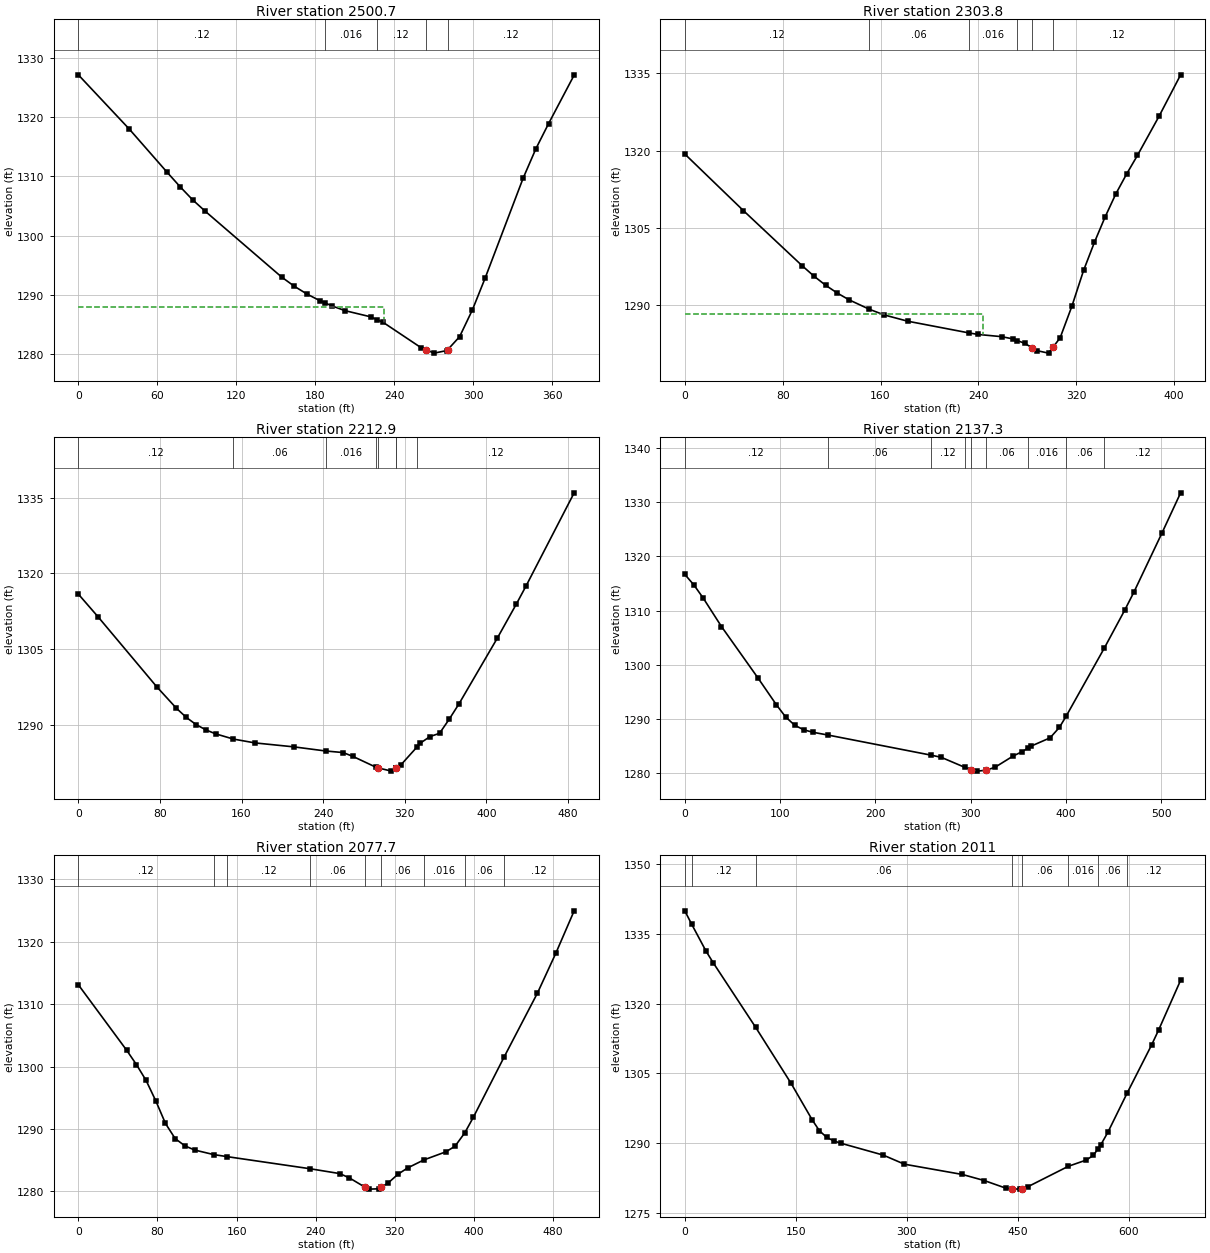
Type RM Length L Ch R = 1 ,2500.7  ,187.3,196.9,206.3
XS GIS Cut Line= 3
     1827310.992      260914.258      1827271.93      260715.473
     1827172.103      260573.112
#Sta/Elev= 28
       0 1327.14    38.6 1318.01    67.5 1310.68    77.2 1308.28    86.8 1306.05
    96.5  1304.1   154.4 1293.02     164 1291.47   173.6 1290.16   183.3 1289.05
  187.16 1288.68   192.9 1288.13   202.6 1287.35   221.9 1286.32  226.571285.858
   231.6 1285.36   260.5 1281.07  263.891280.758   270.2 1280.19   279.9 1280.63
   280.6  1280.8   289.5 1282.96   299.2 1287.47   308.8 1292.79   337.8 1309.73
   347.5  1314.7   357.1 1318.92   376.5  1327.1
#Mann= 5 ,-1 , 0
       0     .12       0  187.16    .016       0  226.57     .12       0
  263.89    .045       0   280.6     .12       0
#XS Ineff= 2 , 0
           232.4 1287.94
Permanent Ineff=
       F       F
Bank Sta=263.89,280.6
XS Rating Curve= 0 ,0
Exp/Cntr=0.3,0.1

Type RM Length L Ch R = 1 ,2303.8  ,62.2,90.9,116.5
XS GIS Cut Line= 3
      1827463.77      260868.251     1827403.006      260547.939
      1827370.02       260475.89
#Sta/Elev= 30
       0 1319.35    47.9 1308.36    95.9 1297.66   105.5 1295.65   115.1 1293.86
   124.7 1292.34   134.2 1291.04  150.911289.194     163  1288.1   182.2 1286.88
  232.481284.596   239.7 1284.31   258.9 1283.88   268.5 1283.43  271.921283.117
   278.1 1282.55  283.581281.762   287.7 1281.17   297.3 1280.68  300.851281.788
   306.8 1283.65   316.4 1289.78     326 1296.76   334.8 1302.18   343.6 1307.14
   352.4 1311.64   361.2 1315.49     370 1319.08   387.7  1326.7   405.3 1334.73
#Mann= 6 ,-1 , 0
       0     .12       0  150.91     .06       0  232.48    .016       0
  271.92     .12       0  283.58    .045       0  300.85     .12       0
#XS Ineff= 2 , 0
          243.55 1288.31
Permanent Ineff=
       F       F
Bank Sta=283.58,300.85
XS Rating Curve= 0 ,0
Exp/Cntr=0.3,0.1

Type RM Length L Ch R = 1 ,2212.9  ,80.3,75.6,77
XS GIS Cut Line= 4
     1827496.756      260852.626     1827473.319      260584.397
     1827529.742      260521.029     1827453.353       260413.39
#Sta/Elev= 30
       0 1315.92    19.2 1311.46    76.9 1297.59    96.2 1293.34   105.8 1291.55
   115.4 1290.13     125 1289.08   134.6 1288.29  152.121287.254   173.1  1286.5
   211.6 1285.71  242.431284.902   259.6 1284.59   269.2 1283.83  291.531281.717
   293.81281.562     307 1280.92  311.111281.473  311.91 1281.58   316.4 1282.19
  331.67 1285.61   335.2 1286.44   344.7 1287.75   354.1 1288.39   363.5 1291.15
     373 1294.16   410.7 1307.19   429.5 1313.98     439 1317.55   486.1 1335.94
#Mann= 8 ,-1 , 0
       0     .12       0  152.12     .06       0  242.43    .016       0
  291.53     .08       0   293.8    .045       0  311.11     .08       0
  311.91    .016       0  331.67     .12       0
Bank Sta=293.8,311.11
XS Rating Curve= 0 ,0
Exp/Cntr=0.3,0.1

Type RM Length L Ch R = 1 ,2137.3  ,78.6,59.7,37.8
XS GIS Cut Line= 4
     1827567.937      260854.362     1827544.499      260586.133
     1827600.923      260522.765     1827502.833      260388.217
#Sta/Elev= 30
       0 1316.67     9.6 1314.71    19.2 1312.34    38.5 1307.06    76.9 1297.56
    96.2 1292.63   105.8 1290.41   115.4 1288.86     125 1288.02   134.6 1287.57
  150.191287.065     2591283.339   269.2 1282.96  294.091281.101  300.561280.701
     307 1280.41  316.411280.571   325.8 1281.13   344.7 1283.19   354.1 1283.99
  360.411284.666   363.9 1285.04   383.5 1286.54   393.3 1288.46  400.29  1290.5
  440.521303.101   461.8 1310.04   471.6 1313.42     501 1324.29   520.6  1331.7
#Mann= 9 ,-1 , 0
       0     .12       0  150.19     .06       0     259     .12       0
  294.09     .06       0  300.56    .045       0  316.41     .06       0
  360.41    .016       0  400.29     .06       0  440.52     .12       0
Bank Sta=300.56,316.41
XS Rating Curve= 0 ,0
Exp/Cntr=0.3,0.1

Type RM Length L Ch R = 1 ,2077.7  ,80.1,66.6,53
XS GIS Cut Line= 3
     1827620.888      260847.418     1827634.777      260485.439
      1827557.52      260369.987
#Sta/Elev= 30
       0 1313.11      49 1302.58    58.7 1300.32    68.5 1297.77    78.3  1294.5
    88.1 1290.87    97.9 1288.45   107.7 1287.29   117.5 1286.62   136.71285.892
  150.581285.553  234.021283.624   264.3 1282.84   274.1 1282.14   290.2 1280.62
   293.7 1280.35   303.5  1280.4  306.441280.681   313.3 1281.35   323.1 1282.74
   332.9 1283.75  349.211285.028   371.5 1286.33   380.8 1287.23  390.66 1289.38
   399.3 1291.87  430.531301.568   464.1 1311.78   482.6 1318.14   501.2 1324.96
#Mann= 9 ,-1 , 0
       0     .12       0   136.7     .06       0  150.58     .12       0
  234.02     .06       0   290.2    .045       0  306.44     .06       0
  349.21    .016       0  390.66     .06       0  430.53     .12       0
Bank Sta=290.2,306.44
XS Rating Curve= 0 ,0
Exp/Cntr=0.3,0.1

Type RM Length L Ch R = 1 ,2011    ,473,436.2,394.2
XS GIS Cut Line= 3
     1828051.444      260787.522     1827762.381      260659.918
     1827589.638       260350.89
#Sta/Elev= 30
       0 1339.91    9.31 1337.03    28.7 1331.25    38.3 1328.78   95.861314.865
   143.6 1302.87   172.4 1294.96   181.9 1292.69   191.5  1291.3   201.1 1290.52
   210.6 1290.02   268.1 1287.46   296.8  1285.5     375  1283.3   404.5    1282
     434 1280.35  441.881280.198   453.6 1280.15  455.431280.244   463.5 1280.66
  518.361285.062   542.2 1286.38     552 1287.38  558.031288.728   561.8 1289.57
   571.7 1292.36  597.591300.733   630.7 1311.08   640.5  1314.4     670 1325.01
#Mann= 8 ,-1 , 0
       0     .06       0    9.31     .12       0   95.86     .06       0
  441.88    .045       0  455.43     .06       0  518.36    .016       0
  558.03     .06       0  597.59     .12       0
Bank Sta=441.88,455.43
XS Rating Curve= 0 ,0
Exp/Cntr=0.3,0.1

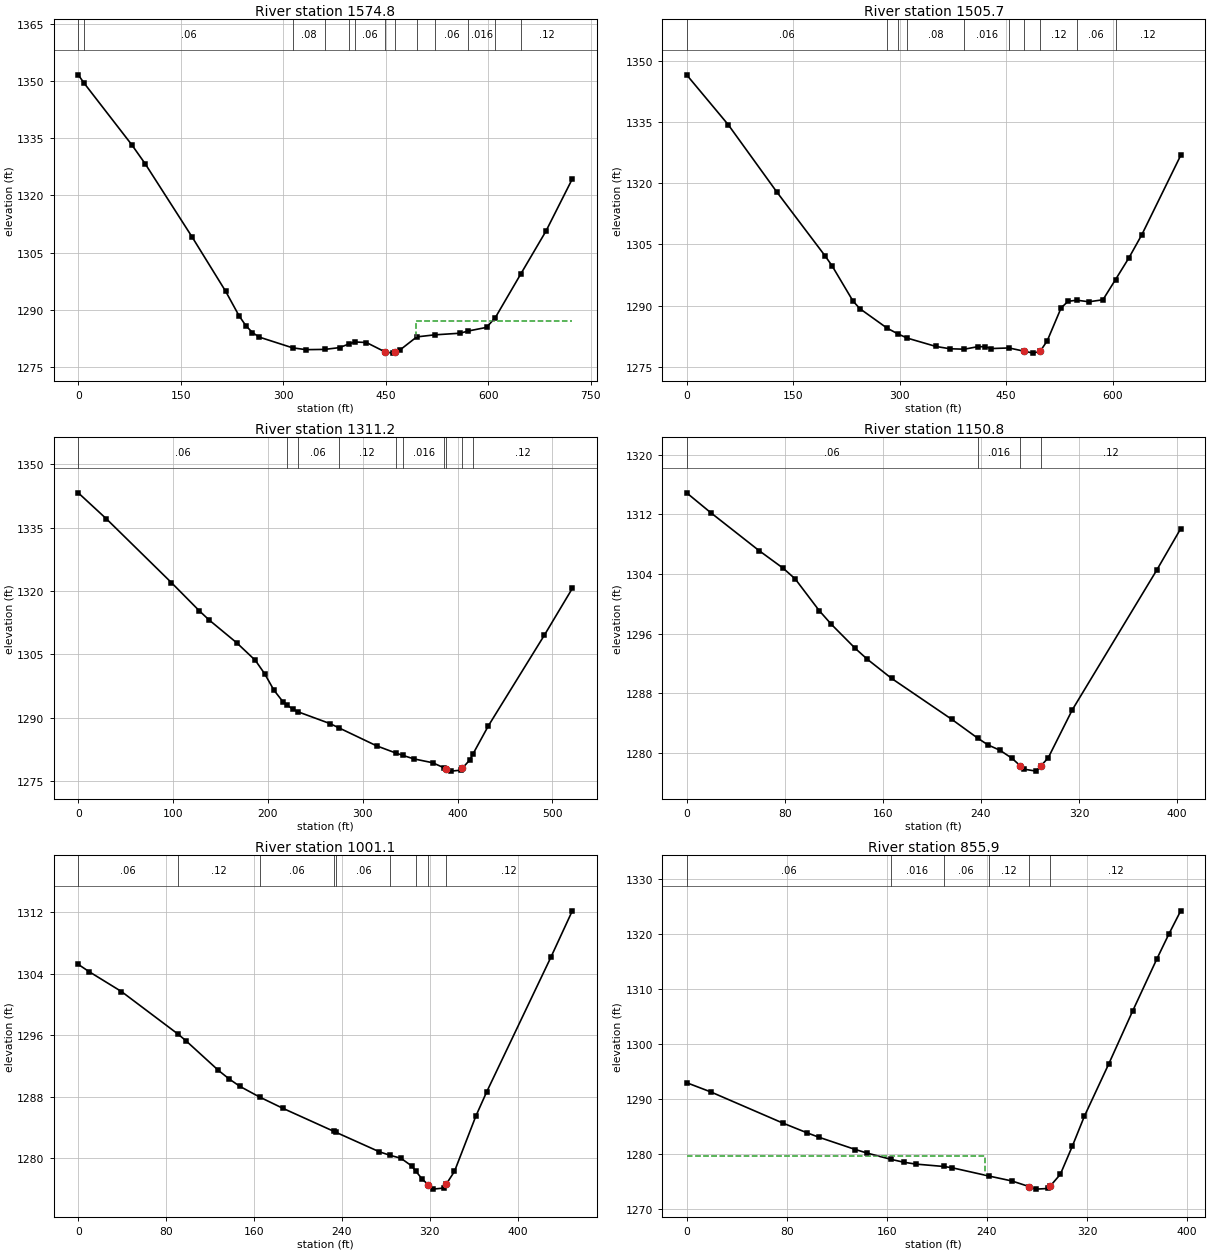
Type RM Length L Ch R = 1 ,1574.8  ,99.4,69,63.2
XS GIS Cut Line= 4
     1828232.867      260481.967      1827843.11      260383.008
     1827712.902      260470.682     1827622.624      260333.529
#Sta/Elev= 30
       0 1351.68    8.821349.439    78.5 1333.28    98.1  1328.3   166.7  1309.1
   215.8 1294.84   235.4 1288.42   245.2 1285.86     255 1284.01   264.8 1282.83
  313.871279.998   333.5 1279.52  360.911279.588   382.5 1280.06  395.941280.996
   405.11281.541   421.8  1281.4   449.3 1278.92     461 1278.61   464.3 1278.88
   470.8 1279.41  495.57 1282.87  521.661283.407   559.1 1283.84  570.651284.405
   597.7 1285.37  610.641287.951   647.8 1299.38   684.7 1310.64   723.3 1324.36
#Mann= 13 ,-1 , 0
       0     .12       0    8.82     .06       0  313.87     .08       0
  360.91     .06       0  395.94     .08       0   405.1     .06       0
   449.3    .045       0   464.3     .12       0  495.57    .016       0
  521.66     .06       0  570.65    .016       0  610.64     .06       0
   647.8     .12       0
#XS Ineff= 2 , 0
                          494.53         1287.03
Permanent Ineff=
       F       F
Bank Sta=449.3,464.3
XS Rating Curve= 0 ,0
Exp/Cntr=0.3,0.1

Type RM Length L Ch R = 1 ,1505.7  ,138.9,194.5,225.3
XS GIS Cut Line= 4
     1828242.416      260427.279     1827826.617      260320.508
     1827696.409      260408.182     1827635.645      260317.036
#Sta/Elev= 30
       0 1346.53    58.5 1334.33   126.8 1317.88   195.1 1302.15   204.9 1299.72
   234.2 1291.14   243.9 1289.26  282.271284.481  297.661283.061  310.761282.037
   351.2 1279.99   370.8 1279.43  390.941279.321   409.8 1279.93   419.5 1279.94
   429.3 1279.48  453.991279.628  475.711278.814   488.2 1278.36     498 1278.84
   507.8 1281.37   527.4 1289.45   537.2 1291.05  549.421291.323   566.6 1290.94
   586.3 1291.43  604.051296.394   622.8 1301.68     641 1307.35   695.8  1326.8
#Mann= 10 ,-1 , 0
       0     .06       0  282.27     .08       0  297.66     .06       0
  310.76     .08       0  390.94    .016       0  453.99     .12       0
  475.71    .045       0     498     .12       0  549.42     .06       0
  604.05     .12       0
Bank Sta=475.71,498
XS Rating Curve= 0 ,0
Exp/Cntr=0.3,0.1

Type RM Length L Ch R = 1 ,1311.2  ,160.8,160.5,160.1
XS GIS Cut Line= 2
      1828236.34      260405.578     1827790.159       260136.48
#Sta/Elev= 30
       0 1343.25    29.5 1337.13    98.3 1321.98   127.8 1315.29   137.6 1313.23
   167.1 1307.75   186.8 1303.58   196.6 1300.41   206.4 1296.52   216.3 1293.67
  220.581292.963   226.1 1292.05  231.861291.404   265.4 1288.63  274.441287.662
   314.6 1283.36  334.811281.661  342.471281.083   353.9 1280.27   373.6 1279.36
  385.771278.152  387.361277.985   393.2 1277.37   403.1 1277.59  404.981278.052
   412.9    1280  416.491281.528   432.6 1288.14   491.6 1309.58     521 1320.62
#Mann= 10 ,-1 , 0
       0     .06       0  220.58     .12       0  231.86     .06       0
  274.44     .12       0  334.81     .06       0  342.47    .016       0
  385.77     .08       0  387.36    .045       0  404.98     .08       0
  416.49     .12       0
Bank Sta=387.36,404.98
XS Rating Curve= 0 ,0
Exp/Cntr=0.3,0.1

Type RM Length L Ch R = 1 ,1150.8  ,158.1,149.7,141.2
XS GIS Cut Line= 2
     1828232.867      260212.001     1827884.777      260008.876
#Sta/Elev= 23
       0 1314.91    19.7 1312.24      59 1307.16    78.6  1304.8    88.5 1303.36
   108.1  1299.1     118 1297.26   137.6 1294.01   147.4 1292.56   167.1    1290
   216.3 1284.49  237.481281.959   245.8 1281.06   255.6 1280.34   265.4 1279.26
  272.141278.256   275.2  1277.8   285.1 1277.54  288.661278.188   294.9 1279.32
   314.6 1285.78   383.4 1304.52     403  1310.1
#Mann= 4 ,-1 , 0
       0     .06       0  237.48    .016       0  272.14    .045       0
  288.66     .12       0
Bank Sta=272.14,288.66
XS Rating Curve= 0 ,0
Exp/Cntr=0.3,0.1

Type RM Length L Ch R = 1 ,1001.1  ,146.1,145.3,144.2
XS GIS Cut Line= 3
     1828286.687       260096.55     1828198.145      259955.057
     1827918.631      259911.654
#Sta/Elev= 27
       0  1305.2     9.8 1304.26    39.3 1301.67   90.991296.118    98.2 1295.25
   127.6 1291.42   137.5 1290.29   147.3 1289.33  165.081287.954   186.4 1286.48
  232.931283.476  235.021283.342   274.2 1280.83  284.181280.363   293.7    1280
   303.5    1279  307.361278.312   313.2 1277.27  318.531276.571     323 1275.98
   332.7 1276.12  335.141276.657   342.5 1278.28     362 1285.48   371.8 1288.61
   430.3 1306.13   449.8 1312.16
#Mann= 9 ,-1 , 0
       0     .06       0   90.99     .12       0  165.08     .06       0
  232.93     .12       0  235.02     .06       0  284.18    .016       0
  307.36     .12       0  318.53    .045       0  335.14     .12       0
Bank Sta=318.53,335.14
XS Rating Curve= 0 ,0
Exp/Cntr=0.3,0.1

Type RM Length L Ch R = 1 ,855.9   ,180.9,196.7,212.6
XS GIS Cut Line= 2
     1828325.749      259817.036     1827933.388      259772.765
#Sta/Elev= 26
       0    1293    19.3 1291.32      77 1285.64    96.3 1283.87   105.9 1283.06
   134.8 1280.84   144.5 1280.17  163.231279.057   173.4 1278.53     183 1278.19
  205.381277.752   211.9 1277.53  241.521276.015     260 1275.11  273.931274.072
   279.3 1273.63   288.9 1273.75  290.491274.173   298.6 1276.32   308.2 1281.45
   317.8 1286.88   337.1 1296.32   356.3    1306   375.6 1315.46   385.2 1319.99
   394.8 1324.28
#Mann= 6 ,-1 , 0
       0     .06       0  163.23    .016       0  205.38     .06       0
  241.52     .12       0  273.93    .045       0  290.49     .12       0
#XS Ineff= 2 , 0
          238.18 1279.63
Permanent Ineff=
       F       F
Bank Sta=273.93,290.49
XS Rating Curve= 0 ,0
Exp/Cntr=0.3,0.1

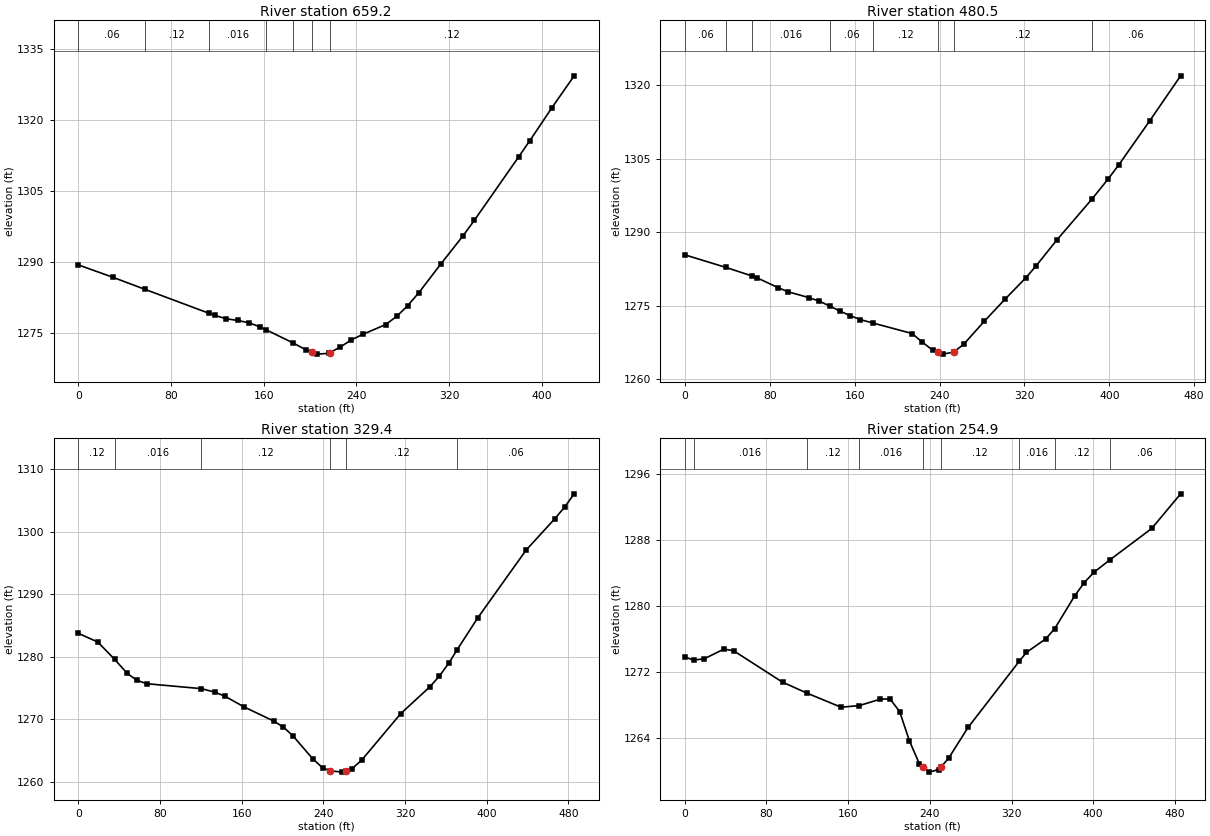
Type RM Length L Ch R = 1 ,659.2   ,193.6,178.6,163.6
XS GIS Cut Line= 3
     1828296.235      259781.012     1828113.944      259588.303
     1827952.485       259567.47
#Sta/Elev= 30
       0 1289.34    29.5 1286.75   57.24  1284.2  112.921279.102   117.9 1278.65
   127.7 1277.96   137.6 1277.59   147.4 1277.11   157.2 1276.19  162.461275.589
  185.621272.813   196.5  1271.4  201.751270.906   206.3 1270.48   216.1 1270.65
  217.411270.823     226 1271.96   235.8  1273.5   245.6 1274.66   265.3 1276.72
   274.8 1278.45   284.4 1280.72     294 1283.47   313.2  1289.6   332.3 1295.53
   341.9 1298.75   380.2 1312.18   389.8 1315.59   408.9 1322.56   428.1  1329.3
#Mann= 7 ,-1 , 0
       0     .06       0   57.24     .12       0  112.92    .016       0
  162.46     .06       0  185.62     .12       0  201.75    .045       0
  217.41     .12       0
Bank Sta=201.75,217.41
XS Rating Curve= 0 ,0
Exp/Cntr=0.3,0.1

Type RM Length L Ch R = 1 ,480.5   ,113.8,151.2,180.4
XS GIS Cut Line= 3
     1828296.235      259669.033     1828228.527      259465.908
     1827978.527      259426.845
#Sta/Elev= 30
       0 1285.36   38.761282.789   62.851281.082    68.1 1280.66    87.6 1278.69
    97.3 1277.82   116.8 1276.63   126.5 1275.93  137.061274.857     146 1273.89
   155.7 1272.96   165.4 1272.14  177.571271.421   214.1  1269.3   223.8 1267.54
   233.6 1265.89   238.4 1265.49   243.3 1265.09   253.4 1265.51   262.8  1267.1
   282.2  1271.8   301.7 1276.29   321.2 1280.64   330.9 1283.07   350.4 1288.35
  383.541296.708     399 1300.87   408.8 1303.69     438 1312.69   467.2  1321.9
#Mann= 8 ,-1 , 0
       0     .06       0   38.76     .12       0   62.85    .016       0
  137.06     .06       0  177.57     .12       0   238.4    .045       0
   253.4     .12       0  383.54     .06       0
Bank Sta=238.4,253.4
XS Rating Curve= 0 ,0
Exp/Cntr=0.3,0.1

Type RM Length L Ch R = 1 ,329.4   ,83.9,74.5,72.5
XS GIS Cut Line= 3
     1828302.312      259553.147     1828202.485      259253.668
     1828034.951      259225.022
#Sta/Elev= 30
       0 1283.76    19.1 1282.36   35.571279.589    47.8 1277.35    57.4 1276.23
      67 1275.69   120.61274.897   133.9 1274.33   143.5 1273.69   162.6 1271.95
   191.3 1269.71   200.9 1268.74   210.4  1267.3   229.6 1263.66   239.2 1262.22
   246.21261.753   258.3 1261.53  261.871261.723   267.8 1262.05   277.4 1263.43
   315.7 1270.89     344 1275.15   353.4 1276.87   362.9    1279  370.941281.121
   391.2 1286.24   438.4 1297.06   466.8 1302.14   476.2 1303.96   485.6  1306.1
#Mann= 6 ,-1 , 0
       0     .12       0   35.57    .016       0   120.6     .12       0
   246.2    .045       0  261.87     .12       0  370.94     .06       0
Bank Sta=246.2,261.87
XS Rating Curve= 0 ,0
Exp/Cntr=0.3,0.1

Type RM Length L Ch R = 1 ,254.9   ,260.7,254.9,249
XS GIS Cut Line= 3
     1828333.562      259476.758     1828233.735      259177.279
     1828066.201      259148.633
#Sta/Elev= 30
       0 1273.82    8.621273.443    19.1  1273.6    38.3 1274.77    47.8 1274.57
    95.7 1270.77  119.231269.468   153.1 1267.74  170.991267.941   191.3 1268.71
   200.9 1268.75   210.4 1267.22     220 1263.67   229.6 1260.93  233.181260.545
   239.2 1259.89   248.7  1260.2  251.191260.553   258.3 1261.56   277.4 1265.29
  327.531273.298   334.6 1274.37   353.4    1276  362.141277.214   381.8  1281.2
   391.2 1282.81   400.7 1284.06  416.411285.571   457.3 1289.36   485.6 1293.55
#Mann= 9 ,-1 , 0
       0     .12       0    8.62    .016       0  119.23     .12       0
  170.99    .016       0  233.18    .045       0  251.19     .12       0
  327.53    .016       0  362.14     .12       0  416.41     .06       0
Bank Sta=233.18,251.19
XS Rating Curve= 0 ,0
Exp/Cntr=0.3,0.1

Chan Stop Cuts=-1
Use User Specified Reach Order=0
Composite Channel Slope=5